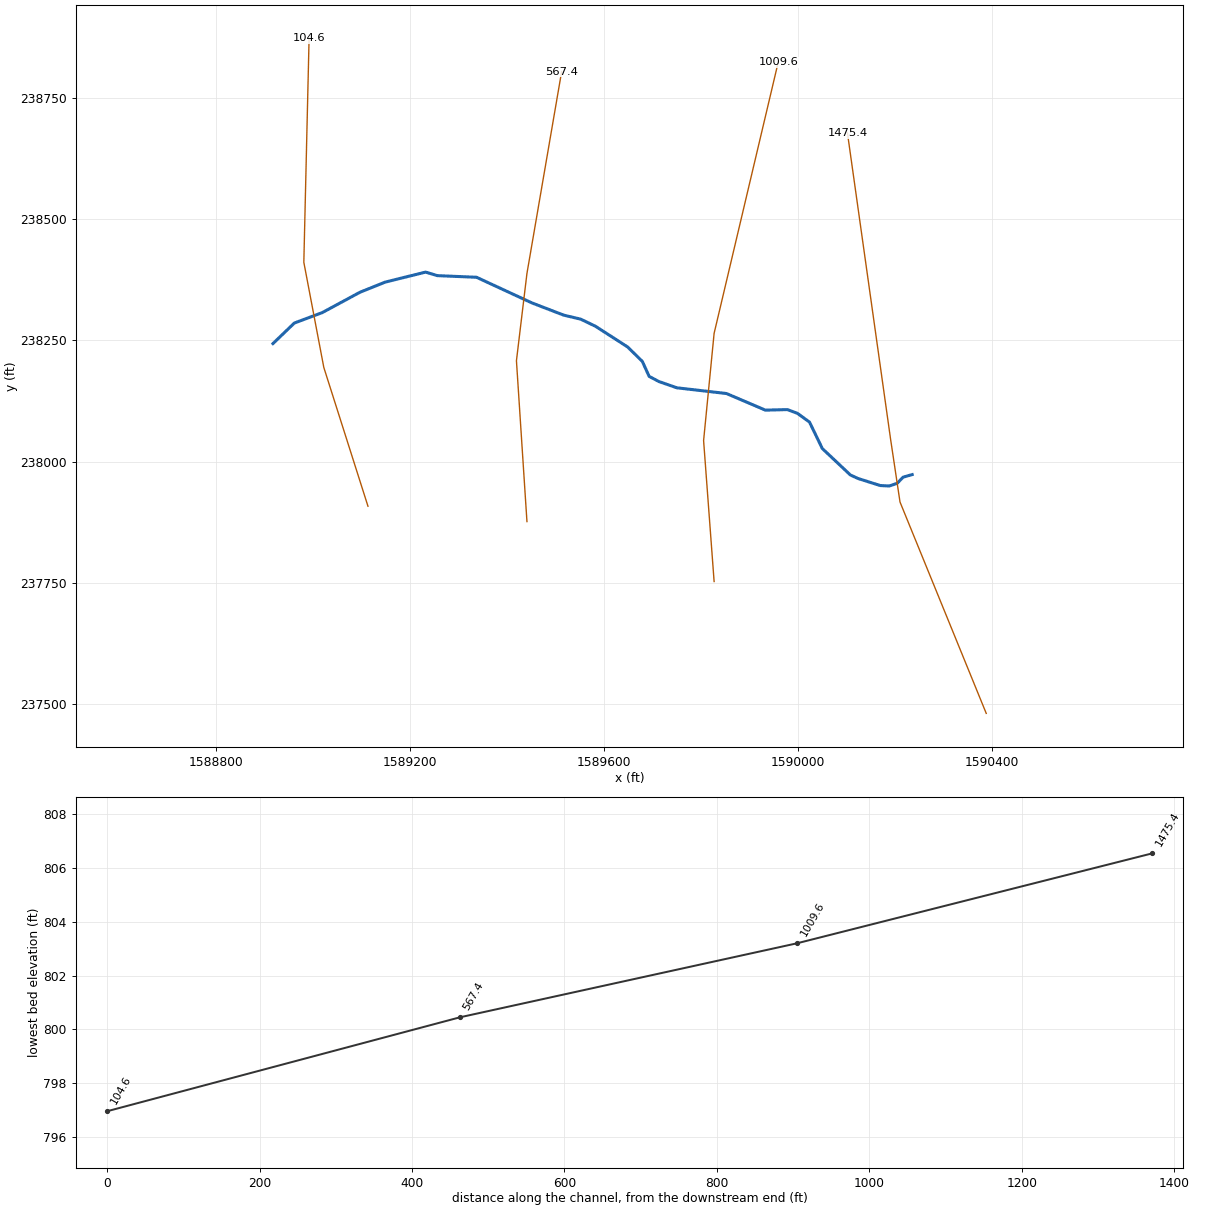
--- STRGHTFR1.prj (project) ---

Proj Title=STRGHTFR1
Current Plan=p01
Default Exp/Contr=0,0
English Units
Geom File=g01
Flow File=f01
Plan File=p01
BEGIN DESCRIPTION:
END DESCRIPTION:
DSS Export Rating Curves= 0
DSS Export Rating Curve Sorted= 0
DSS Export Volume Flow Curves= 0
DXF OffsetX= 0
DXF OffsetY= 0
DXF ScaleX= 0
DXF ScaleY= 0

--- STRGHTFR1.p01 (plan) ---

Plan Title=Floodplain
Program Version=4.00
Geom File=g01
Flow File=f01
K Sum by GR=0
Std Step Tol=0.01
Critical Tol=0.01
Num of Std Step Trials=20
Max Error Tol=0.3
Flow Tol Ratio=0.001
Split Flow NTrial=30
Split Flow Tol=0.02
Split Flow Ratio=0.02
Log Output Level=0
Friction Slope Method=1
Unsteady Friction Slope Method=2
Unsteady Bridges Friction Slope Method=1
Global Log Level=0
CheckData=False
Run HTab=0
Run UNet=0
Run PostProcess=0
UNET Theta=0
UNET Theta Warmup=0
UNET ZTol=0
UNET ZSATol=0
UNET MxIter=0
UNET MaxInSteps=0
UNET DtIC=0
UNET DtMin=0
UNET MaxCRTS=0
UNET WFStab=0
UNET SFStab=0
UNET WFX=0
UNET SFX=0
UNET DSS MLevel=0
UNET DZMax Abort=0
UNET Convert EG Bridges=0
UNET Use Existing IB Tables=0
UNET Froude Limit=0
UNET Froude Power=0
Write IC File=0
Echo Input=False
Echo Output=False
Write Detailed=0

--- STRGHTFR1.f01 (steady flow) ---

Flow Title=NFF Regression Equation
Program Version=4.10
Number of Profiles= 1
Profile Names=P100yr
River Rch & RM=STRGHTFR1,Main            ,1475.4
1162.633
River Rch & RM=STRGHTFR1,Main            ,104.6
1197.249
Boundary for River Rch & Prof#=STRGHTFR1,Main            , 1
Up Type= 0
Dn Type= 3
Dn Slope=0.00765
DSS Import GetInterval= 0
DSS Import GetPeak= 0
DSS Import FillOption= 0

--- STRGHTFR1.g01 (geometry) ---

Geom Title=USGS 10m DEM
Program Version=4.10

River Reach=STRGHTFR1       ,Main
Reach XY= 30
     1590236.096      237973.198      1590217.43      237967.902
     1590205.277      237955.316     1590188.784      237949.673
     1590170.343      237950.601     1590124.264      237965.211
      1590108.53      237972.516      1590050.65      238027.025
     1590024.238      238081.533     1589999.513      238099.515
     1589978.721      238107.382     1589933.204      238106.258
     1589852.846      238140.537     1589750.573      238152.338
     1589713.484      238165.262     1589693.255      238175.939
     1589679.206      238206.846     1589648.861      238236.629
     1589582.552      238279.337     1589552.207      238293.947
     1589516.804      238302.376     1589451.057      238327.664
     1589336.983      238380.486     1589256.063      238383.858
       1589231.9      238391.163      1589148.17      238370.371
     1589096.472       238349.58     1589018.362      238307.434
     1588961.043       238286.08     1588916.842      238243.624

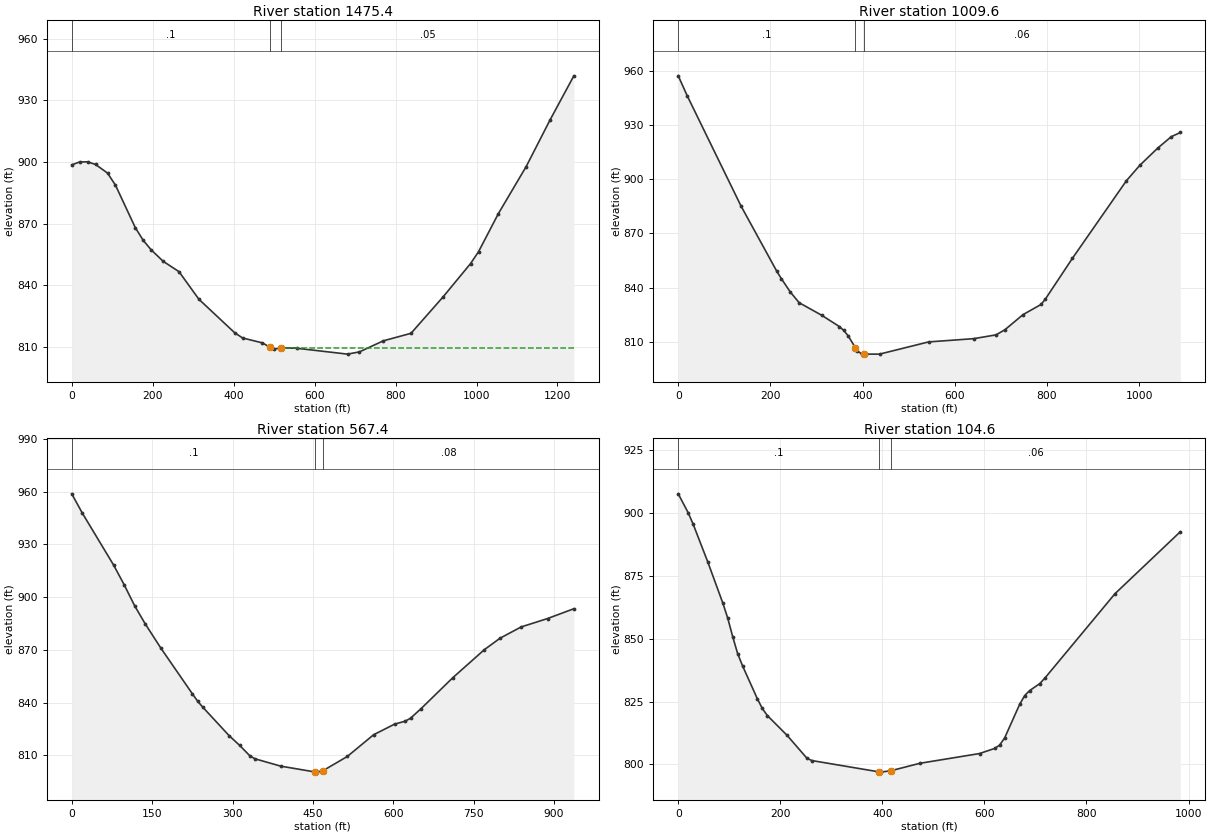
Type RM Length L Ch R = 1 ,1475.4  ,470.5,465.8,461.9
XS GIS Cut Line= 4
     1590388.989      237480.399     1590211.038      237916.597
     1590191.507      238046.806     1590102.531      238678.316
#Sta/Elev= 30
       0  898.61    19.6  900.04    39.3  900.07    58.9  898.79    88.3  894.62
     108  888.72     157  868.05   176.7  861.84   196.3  857.25   225.7  851.72
     265  846.64   314.1  833.23   402.4  816.95     422   814.4   471.1  812.01
   489.9  809.85   499.3     809   517.7  809.58   555.7   809.4   681.3  806.54
   710.7  807.63   769.6     813   838.2  816.67   916.7  834.22   985.4  850.61
    1005  856.36  1054.1  874.92  1122.8  897.81  1181.6  920.42  1240.5  941.92
#Mann= 3 , 0 , 0
       0      .1       0   489.9    .045       0   517.7     .05       0
#XS Ineff= 2 , 0
                          527.28          809.75
Permanent Ineff=
       F       F
Bank Sta=489.9,517.7
XS Rating Curve= 0 ,0
Exp/Cntr=0.3,0.1

Type RM Length L Ch R = 1 ,1009.6  ,442.5,442.2,441.3
XS GIS Cut Line= 4
     1589827.358      237752.535     1589805.656      238043.333
     1589827.346      238264.689     1589959.736      238824.583
#Sta/Elev= 30
       0  957.18    19.4  946.19   136.1   885.2   213.8  849.07   223.6  845.02
     243  837.63   262.4  831.64     311  824.75   349.6  818.46   359.3  816.28
     369  813.22  384.37806.7283   388.4  804.95     398  803.34   403.4  803.26
   407.6   803.2   436.7   803.2   543.3  809.96   640.8  811.75   689.6  813.85
     709  816.72   748.1  825.05   787.1  830.67   796.8  833.73   855.3  856.22
   972.3   899.1  1001.6  907.69  1040.6  917.25  1069.8   923.5  1089.4  925.83
#Mann= 3 , 0 , 0
       0      .1       0  384.37    .045       0   403.4     .06       0
Bank Sta=384.37,403.4
XS Rating Curve= 0 ,0
Exp/Cntr=0.3,0.1

Type RM Length L Ch R = 1 ,567.4   ,455.8,462.8,469.5
XS GIS Cut Line= 4
     1589441.073      237876.233     1589419.371      238208.264
     1589441.061      238388.387     1589512.687      238805.052
#Sta/Elev= 30
       0   958.7    19.6  947.78    78.3  918.09    97.9  906.92   117.4  895.02
     137  884.78   166.4   870.9   225.1  844.97   234.9  840.76   244.7   837.3
   293.6   821.2   313.2  815.69   332.7  809.61   342.3  807.99     390  803.85
     454  800.54   456.9  800.45     469  801.31   514.2  809.36   563.3  821.72
   602.6  827.77   622.3  829.43   632.2  831.13   651.8  836.55   710.8  854.08
   769.8  870.06   799.3  876.62   838.6  883.01   887.8  887.78   936.9  893.36
#Mann= 3 , 0 , 0
       0      .1       0     454    .045       0     469     .08       0
Bank Sta=454,469
XS Rating Curve= 0 ,0
Exp/Cntr=0.3,0.1

Type RM Length L Ch R = 1 ,104.6   ,91.3,104.6,117.6
XS GIS Cut Line= 4
     1589112.948      237907.917     1589021.802      238194.375
     1588980.569      238411.389      1588991.42      238873.629
#Sta/Elev= 30
       0  907.52    19.4  900.04    29.1  895.53    58.2   880.3    87.3  864.16
      97  858.14   106.7   850.8   116.4  844.06   126.1  839.15   155.2  826.03
   164.8  822.24   174.6  819.44   213.3  811.58   252.1   802.5   261.8  801.56
   393.5797.0601   396.6  796.96     417  797.53   473.5  800.47   590.4  804.34
   619.9  806.36   629.7  807.66   639.6  810.52   669.1   823.9   678.9  827.36
   688.7  829.36   708.4  832.11   718.3  834.27     856  867.87   983.9  892.46
#Mann= 3 , 0 , 0
       0      .1       0   393.5    .045       0     417     .06       0
Bank Sta=393.5,417
XS Rating Curve= 0 ,0
Exp/Cntr=0.3,0.1

Chan Stop Cuts=-1
Use User Specified Reach Order=0
Composite Channel Slope=5